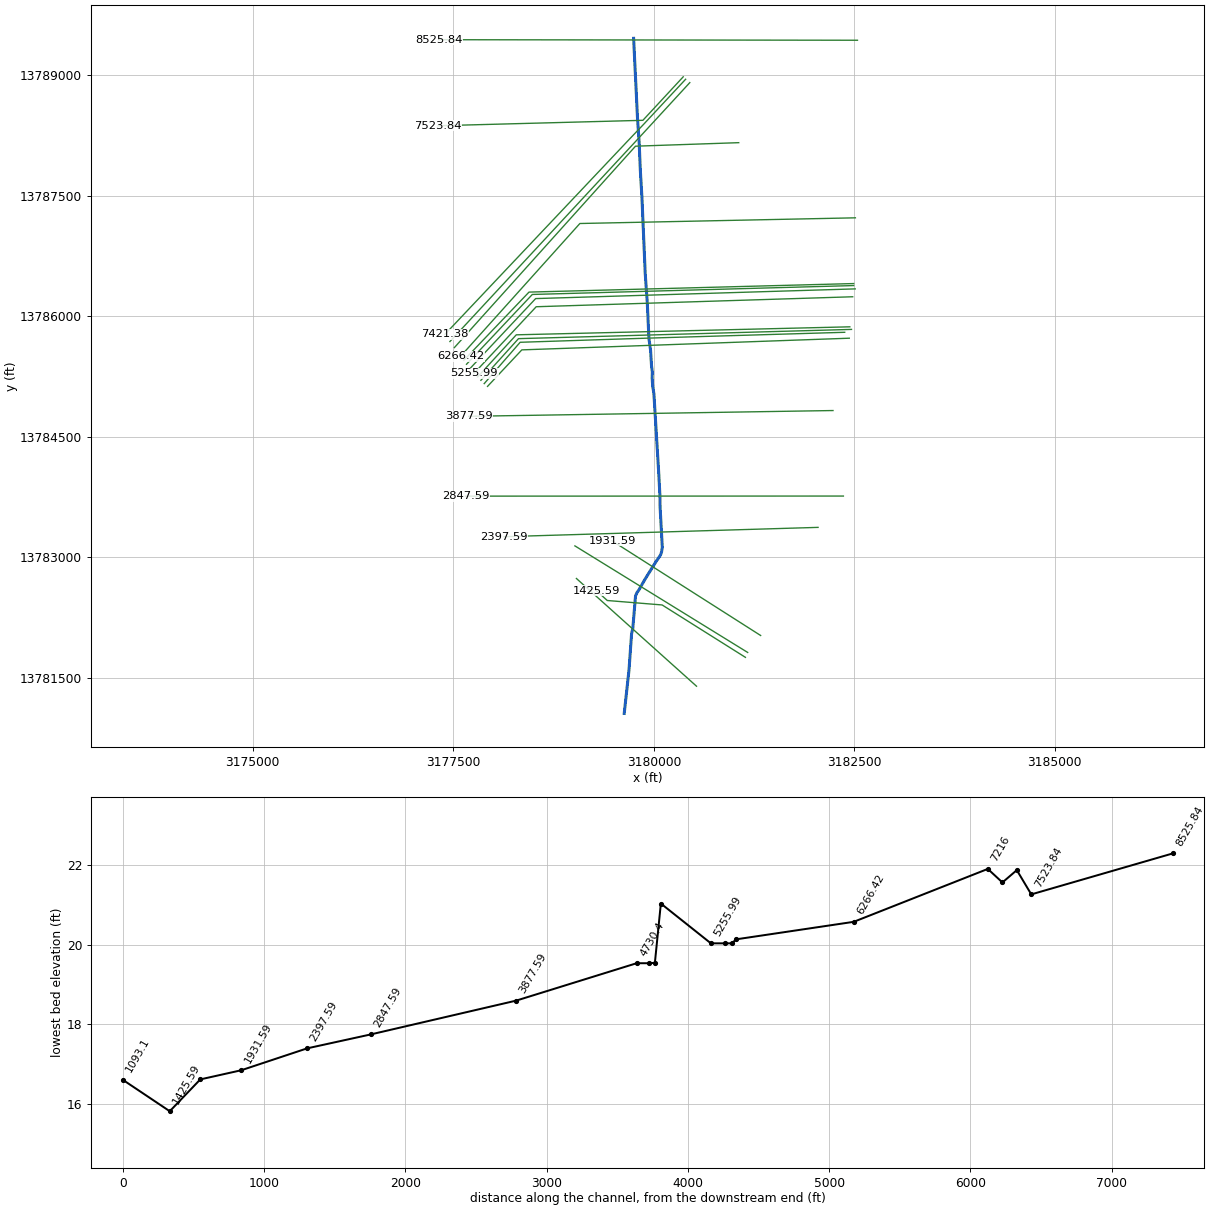
--- A119-05-00.prj (project) ---

Proj Title=A119_05_00
Current Plan=p04
Default Exp/Contr=.3,.1
English Units
Geom File=g06
Flow File=f02
Flow File=f03
Plan File=p02
Plan File=p04
Y Axis Title=Elevation
X Axis Title(PF)=Main Channel Distance
X Axis Title(XS)=Station
BEGIN DESCRIPTION:
Watershed:  Clear Creek
Stream Name:  Unnamed Tributary to Turkey Creek
HCFCD Unit A119-05-00
[Flood Hazard, Floodway] Model
10, 2, 1, 0.2% Event
Filename:	A119-05-00.prj
Prepared by:  Arcadis,CLK,SDS,AML  	DATE:  09/2003
Reviewed by: JB			DATE:  09/2003
STATUS [Final RAS]
END DESCRIPTION:
DSS Export Rating Curves= 0
DSS Export Rating Curve Sorted= 0
DSS Export Volume Flow Curves= 0
DXF Filename=V:\TSARP\GIS\A119-05-00\7421.38.dxf
DXF OffsetX= 0
DXF OffsetY= 0
DXF ScaleX= 1
DXF ScaleY= 10

--- A119-05-00.p04 (plan) ---

Plan Title=Floodway
Version=Version 3.0.1  Mar 2001
Short Identifier=Floodway0607
Geom File=g06
Flow File=f03
Subcritical Flow
K Sum by GR= 0
Std Step Tol= 0.01
Critical Tol= 0.01
Num of Std Step Trials= 20
Max Error Tol= 0.3
Flow Tol Ratio= 0.001
Split Flow NTrial= 30
Split Flow Tol= 0.02
Split Flow Ratio= 0.02
Log Output Level= 0
Friction Slope Method= 0
Unsteady Friction Slope Method= 2
Secant Critical Depth
Global Vel Dist= 0 , 0 , 0
Global Log Level= 0
CheckData=True
Encroach Param=-1 ,0,0, 2
Encroach River=A119-05-00
Encroach Reach=1
Encroach Node=8525.84
       1 4957.08 5047.85
Encroach Node=7523.84
       1 4948.39  5055.3
Encroach Node=7421.38
       13422.0643544.854
Encroach Node=7345.98
       4       1
Encroach Node=7319.6
       1 3522.08 3649.46
Encroach Node=7216
       1 4951.27 5055.78
Encroach Node=6266.42
       1 4955.62 5037.36
Encroach Node=5433.46
       1  4971.4 5059.54
Encroach Node=5404.87
       1 4959.45 5049.99
Encroach Node=5380.465
       1 4959.45    5565
Encroach Node=5356.06
       1 4959.45 5049.99
Encroach Node=5255.99
       1 4959.45 5049.99
Encroach Node=4901.79
       1 4943.27 5034.96
Encroach Node=4859.47
       1  4947.3 5034.35
Encroach Node=4840.31
       4       1
Encroach Node=4821.15
       1 4953.65 5034.58
Encroach Node=4730.4
       1  4948.2  5051.9
Encroach Node=3877.59
       1  4948.1 5047.72
Encroach Node=2847.59
       1 4951.44 5049.58
Encroach Node=2397.59
       1 4925.89 5041.95
Encroach Node=1931.59
       1 4942.05 5039.39
Encroach Node=1641.59
       1 4957.42 5045.44
Encroach Node=1425.59
       1 4953.04 5038.93
Encroach Node=1093.1
       14279.0564377.299
Encroach Node=1042.26
       14302.0074409.714
Encroach Node=791.48
       4       1
Encroach Node=566.98
       14063.0624169.167
Encroach Node=411.98
       1 4960.82 5046.89
Encroach Node=170.98
       1 4960.82 5046.89
Encroach Reach=A119-05-00_0002
Encroach Node=8525.84
       1 4957.08 5047.85
Encroach Node=7523.84
       1 4948.39  5055.3
Encroach Node=7421.38
       13422.0643544.854
Encroach Node=7345.98
       4       1
Encroach Node=7319.6
       1 3522.08 3649.46
Encroach Node=7216
       1 4951.27 5055.78
Encroach Node=6266.42
       1 4955.62 5037.36
Encroach Node=5433.46
       1  4971.4 5059.54
Encroach Node=5404.87
       1 4959.45 5049.99
Encroach Node=5380.465
       1 4959.45    5565
Encroach Node=5356.06
       1 4959.45 5049.99
Encroach Node=5255.99
       1 4959.45 5049.99
Encroach Node=4901.79
       1 4943.27 5034.96
Encroach Node=4859.47
       1  4947.3 5034.35
Encroach Node=4840.31
       4       1
Encroach Node=4821.15
       1 4953.65 5034.58
Encroach Node=4730.4
       1  4948.2  5051.9
Encroach Node=3877.59
       1  4948.1 5047.72
Encroach Node=2847.59
       1 4951.44 5049.58
Encroach Node=2397.59
       1 4925.89 5041.95
Encroach Node=1931.59
       1 4942.05 5039.39
Encroach Node=1641.59
       1 4957.42 5045.44
Encroach Node=1425.59
       1 4953.04 5038.93
Encroach Node=1093.1
       14279.0564377.299
Encroach Node=1042.26
       14302.0074409.714
Encroach Node=791.48
       4       1
Encroach Node=566.98
       14063.0624169.167
Encroach Node=411.98
       1 4960.82 5046.89
Encroach Node=170.98
       1 4960.82 5046.89
BEGIN DESCRIPTION:
TCB Denver office revised n values, bridges, & floodway.   TCB Austin office revised:  (1) placement of blocked obstructions to only occur when crossection goes outside of drainage basin boundary; (2) placement of effective flow areas; (3) changed some contr/expan coeffs.; (4) created improved deck/roadway profiles at culverts; (5) xxxxxxx
END DESCRIPTION:
Computation Interval=1HOUR
Output Interval=1HOUR
Run HTab= 0
Run UNet= 0
Run PostProcess= 0
UNET Theta= 1
UNET ZTol= 0.02
UNET ZSATol= 0.1
UNET MxIter= 20
UNET MaxInSteps= 20
UNET DtIC= 0
UNET DtMin= 0
UNET MaxCRTS= 20
UNET WFStab= 2
UNET SFStab= 1
UNET WFX= 1
UNET SFX= 1
UNET Convert EG Bridges=-1
UNET Use Existing IB Tables=-1
Instantaneous Interval=1HOUR
DSS File=dss
Write IC File= 0
Write Velocity= 0
Write Detailed= 0

--- A119-05-00.p02 (plan) ---

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Plan Title=FEMA Effective June 2007
Short Identifier=FEMAeff0607
Geom File=g06
Flow File=f02
TCB Denver office revised n values, bridges, & floodway.   TCB Austin office revised:  (1) placement of blocked obstructions to only occur when crossection goes outside of drainage basin boundary; (2) placement of effective flow areas; (3) changed some contr/expan coeffs.; (4) created improved deck/roadway profiles at culverts; (5) changed manning's n values in the upstream right overbank to simulate ineffective flow areas

--- A119-05-00.f03 (steady flow) ---

Flow Title=Floodway
Version=Version 3.0.1  Mar 2001
Number of Profiles= 2
Profile Names=1PCT_100yr, 1PCTFloodway_100yrFW
River Rch & RM=A119-05-00,A119-05-00_0002               ,8525.84
     893     893
River Rch & RM=A119-05-00,A119-05-00_0002               ,7523.84
     941     941
River Rch & RM=A119-05-00,A119-05-00_0002               ,5433.46
    1013    1013
River Rch & RM=A119-05-00,A119-05-00_0002               ,4859.47
    1112    1112
River Rch & RM=A119-05-00,A119-05-00_0002               ,4730.4
    1320    1320
River Rch & RM=A119-05-00,A119-05-00_0002               ,2847.59
    1423    1423
River Rch & RM=A119-05-00,A119-05-00_0002               ,1093.10
    1501    1501
Boundary for River Rch & Prof#=A119-05-00,A119-05-00_0002               , 1
Up Type= 0
Dn Type= 3
Dn Slope=.0009
Boundary for River Rch & Prof#=A119-05-00,A119-05-00_0002               , 2
Up Type= 0
Dn Type= 3
Dn Slope=.0009
DSS Import GetInterval= 0
DSS Import GetPeak= 0
DSS Import FillOption= 0

--- A119-05-00.f02 (steady flow) ---

Flow Title=FEMA Effective June 2007
Version=Version 3.0.1  Mar 2001
Number of Profiles= 4
Profile Names=10PCT_10yr, 2PCT_50yr, 1PCT_100yr, 0.2PCT_500yr
River Rch & RM=A119-05-00,A119-05-00_0002               ,8525.84
     530     771     893    1240
River Rch & RM=A119-05-00,A119-05-00_0002               ,7523.84
     560     814     941    1303
River Rch & RM=A119-05-00,A119-05-00_0002               ,5433.46
     605     879    1013    1398
River Rch & RM=A119-05-00,A119-05-00_0002               ,4859.47
     669     968    1112    1524
River Rch & RM=A119-05-00,A119-05-00_0002               ,4730.4
     807    1162    1320    1777
River Rch & RM=A119-05-00,A119-05-00_0002               ,2847.59
     881    1262    1423    1890
River Rch & RM=A119-05-00,A119-05-00_0002               ,1093.10
     941    1342    1501    1966
Boundary for River Rch & Prof#=A119-05-00,A119-05-00_0002               , 1
Up Type= 0
Dn Type= 3
Dn Slope=.0009
Boundary for River Rch & Prof#=A119-05-00,A119-05-00_0002               , 2
Up Type= 0
Dn Type= 3
Dn Slope=.0009
Boundary for River Rch & Prof#=A119-05-00,A119-05-00_0002               , 3
Up Type= 0
Dn Type= 3
Dn Slope=.0009
Boundary for River Rch & Prof#=A119-05-00,A119-05-00_0002               , 4
Up Type= 0
Dn Type= 3
Dn Slope=.0009
DSS Import GetInterval= 0
DSS Import GetPeak= 0
DSS Import FillOption= 0

--- A119-05-00.g06 (geometry) ---

Geom Title=A119-05-00 June 2007
Version=Version 3.0.1  Mar 2001

River Reach=A119-05-00      ,A119-05-00_0002
Reach XY= 30
      3179748.31      13789460.8      3179797.76      13788447.7
      3179817.31      13788169.4      3179832.26       13787814.
      3179851.81      13787485.2      3179893.21      13786528.4
      3179918.51      13786171.9      3179939.21      13785723.4
      3179959.91      13785572.8      3179971.41      13785385.3
      3179981.75       13785306.      3179979.46       13785229.
      3179986.35      13785126.6       3180001.3      13785034.6
      3180062.25       13784033.      3180076.05      13783773.1
      3180078.35      13783624.8      3180105.95      13783122.2
      3180096.75      13783064.7      3180087.55       13783036.
      3180073.75      13783010.7      3180032.35       13782952.
      3179890.91      13782725.5      3179813.86       13782591.
      3179788.56      13782555.3      3179772.46      13782518.5
      3179737.96      13782111.4      3179723.02       13782047.
      3179690.82      13781593.9      3179631.24      13781054.1

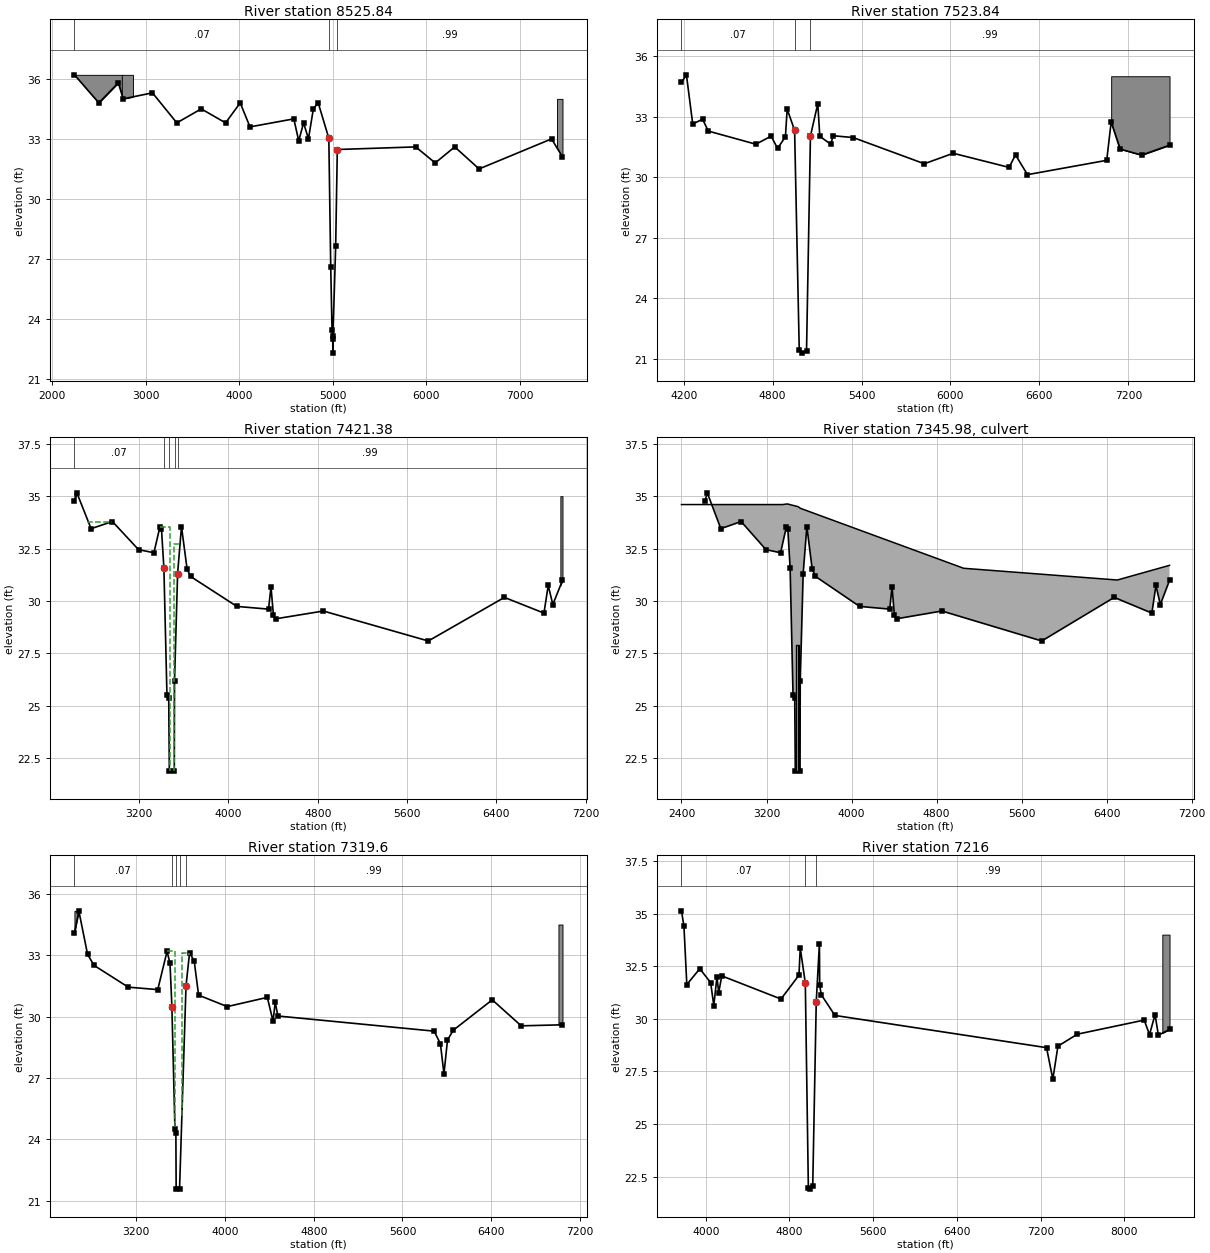
Type RM Length L Ch R = 1 ,8525.84 ,994,1002,1014
BEGIN DESCRIPTION:
v1 - x-section, left bank station to right bank station survey data, overbank station and elevations from DEM.  Blocked obstructions marks where x-section goes outside of drainage basin boundary.
END DESCRIPTION:
XS GIS Cut Line= 3
      3182539.21       13789437.      3177844.64      13789443.1
 3177317.540347313789443.7848993
#Sta/Elev= 30
  2235.5    36.2  2496.3    34.8  2704.9    35.8  2757.1      35  3070.1    35.3
  3330.9    33.8  3591.7    34.5  3852.5    33.8    4009    34.8  4113.3    33.6
  4582.7      34  4634.9    32.9    4687    33.8  4739.2      33  4791.4    34.5
  4843.5    34.8 4957.08   33.03 4977.41    26.6 4991.49   23.44 4998.96   23.17
    5000    22.3 5000.15   23.03 5030.25   27.64 5047.85   32.47  5886.7    32.6
  6095.4    31.8    6304    32.6  6564.8    31.5    7340      33    7457    32.1
#Mann= 3 , 0 , 0
  2235.5     .07       0 4957.08     .04       0 5047.85     .99       0
#XS Ineff= 2 ,-1
    4009  4843.5    34.8
Permanent Ineff=
       F       F
#Block Obstruct= 3 ,-1
 2234.73 2745.32    36.2 2741.66  2861.4    36.2  7398.5    7457      35
Bank Sta=4957.08,5047.85
XS Rating Curve= 0
Exp/Cntr=.3,.1

Type RM Length L Ch R = 1 ,7523.84 ,52.61,102.46,420.41
BEGIN DESCRIPTION:
sv1u - upstream structure valley 1, overbank stations and elevations from DEM.  High C/E coeffients used to account for pipe crossing just d/s of bridge.  Blocked obstruction marks where x-section goes outside of drainage basin boundary.
END DESCRIPTION:
XS GIS Cut Line= 3
     3180366.866    13788981.749     3179864.001    13788439.882
     3177311.616    13788372.192
#Sta/Elev= 30
  4185.2   34.69 4218.57   35.07 4261.19   32.63 4327.35   32.87 4366.46   32.28
  4687.1   31.63 4790.42   32.03 4833.47   31.42 4886.54      32 4898.21   33.37
 4948.39   32.32 4979.73   21.43    5000   21.27 5028.86   21.38  5055.3   32.04
 5104.93   33.64 5118.35   32.02 5192.39   31.63 5208.38   32.05 5343.43   31.96
  5823.6   30.66 6018.67   31.18 6395.19   30.48 6438.81    31.1 6519.46   30.12
 7054.03   30.83 7084.04   32.73 7144.06   31.39 7289.21   31.09 7477.73   31.58
#Mann= 3 , 0 , 0
  4185.2     .07       0 4948.39     .04       0  5055.3     .99       0
#XS Ineff= 2 ,-1
    4240 4898.21   33.37
Permanent Ineff=
       F       F
#Block Obstruct= 1 ,-1
 7084.04 7477.73      35
Bank Sta=4948.39,5055.3
XS Rating Curve= 0
Exp/Cntr=.5,.3

Type RM Length L Ch R = 1 ,7421.38 ,101.14,101.78,102.06
BEGIN DESCRIPTION:
s1u - upstream x-section of structure 1, scarsdale rd, 1-10x10 box culver, 2- 10x10 box culverts throttled to 6x10, overbank station and elev. from DEM. Composite manning's n value of 0.025 used for the channel area which consists of concrete side slopes with a highly vegetated channel bottom.  Blocked obstruction marks where x-section goes outside of drainage basin boundary.  Manning's n value of 0.06 was used instead of the previous 0.025 because of excessive growth in the channel.
END DESCRIPTION:
XS GIS Cut Line= 4
     3180396.805    13788951.296     3179868.819    13788385.335
     3179729.643    13788240.361     3177396.092    13785774.464
#Sta/Elev= 30
2621.134   34.772642.814   35.162770.174   33.452961.204   33.793194.694   32.45
3332.654    32.33385.724   33.523400.404   33.443422.064   31.573449.384   25.52
3465.384   25.36 3470.82   21.88 3515.24   21.883517.194   26.183544.854   31.31
3579.574   33.553629.734   31.523660.804   31.174075.384   29.744359.144   29.61
4380.964   30.684402.784   29.324424.614   29.154849.954   29.525789.424   28.09
6470.934   30.176825.144   29.426863.314   30.746904.624   29.83 6991.11   30.98
#Mann= 5 ,-1 , 0
2621.134     .07       03422.064    .015       03465.384     .06       0
3517.194    .015       03544.854     .99       0
#XS Ineff= 3 ,-1
    2730 2960.69   33.79 3385.72 3481.04   33.52 3511.24    3580    32.7
Permanent Ineff=
       F       F       F
#Block Obstruct= 2 ,-1
 2621.13 2642.81   35.16 6972.08 6991.11      35
Bank Sta=3422.064,3544.854
XS Rating Curve= 0
Skew Angle= 45
Exp/Cntr=.5,.3

Type RM Length L Ch R = 2 ,7345.98 ,,,
Node Photo=A119-05-S1p1.JPG
BEGIN DESCRIPTION:
s1 - Scarsdale Blvd.
Road profile ends abruptly because of the orientation of the bounding cross-sections (i.e. they cross over the roadway in the overbank areas). This was the most accurate way to reflect this structure and cross-section orientation.
END DESCRIPTION:
Bridge Culvert--1,0,-1,-1, 0
Deck Dist Width WeirC Skew NumUp NumDn MinLoCord MaxHiCord MaxSubmerge Is_Ogee
6,82,2.6,45, 9, 9, 31, , .95, 0, 0,0,,
    2400 2621.13 3350.89  3396.4 3496.72 3519.43 5054.57    6500 6991.11
    34.6    34.6    34.6   34.63    34.5   34.42   31.56      31    31.7
      20      20      20      20      20      20      20      20      20
    2400    2644 3350.89  3396.4 3496.72 3519.43 5054.57    6500 7041.97
    34.6    34.6    34.6   34.63    34.5   34.42   31.56      31    31.7
      20      20      20      20      20      20      20      20      20
BR Coef=-1 , 1 , 1 ,, 0 ,,,.8,0,,0,
WSPro=,,,, 1 ,,,, 0 ,,,, 0 ,,,,-1 ,-1 ,-1 , 0 , 0 , 0 , 0 , 0
Multiple Barrel Culv=2,6,10,82,.013,.7,1,8,3,21.88,21.57, 2,Culvert #1  , 0 ,6
 3487.04 3573.94 3505.24    3586
Culvert Bottom n=.013
BC Design=,, 0 ,, 0 ,,,,,,
BC HTab HWMax=35

Type RM Length L Ch R = 1 ,7319.6  ,333.57,103.6,63.04
BEGIN DESCRIPTION:
s1d- downstream x-section of structure 1, scarsdale rd, 1-10x10 box culver, 2- 10x10 box culverts throttled to 6x10, overbank station and elev. from DEM.   Composite manning's n value of 0.025 used for the channel area which consists of concrete side slopes with a highly vegetated channel bottom.   Blocked obstruction marks where x-section goes outside of drainage basin boundary.  Manning's n value of 0.04 was used instead of the previous 0.025 because of excessive growth in the channel but less than u/s.
END DESCRIPTION:
XS GIS Cut Line= 3
     3180448.958    13788909.278     3179815.994    13788222.791
     3177458.152    13785684.822
#Sta/Elev= 30
    2644   34.08 2683.47   35.17 2762.32   33.04 2821.47    32.5 3129.03   31.44
  3394.7   31.32 3478.53   33.19 3505.21    32.6 3522.08   30.49 3549.47   24.53
 3558.04   24.313560.565   21.573591.091   21.57 3649.46   31.51 3681.46   33.12
 3723.07   32.72 3762.72   31.05 4020.94   30.49 4381.81   30.94 4433.65   29.78
 4453.16    30.7 4477.33   30.03 5885.65   29.29 5942.03   28.67 5973.81    27.2
 6005.72   28.86 6058.78   29.34 6409.04   30.82 6670.06   29.55 7041.97    29.6
#Mann= 5 ,-1 , 0
    2644     .07       0 3522.08    .015       0 3558.04     .04       0
3591.091    .015       0 3649.46     .99       0
#XS Ineff= 3 ,-1
    2720 3478.53   33.19 3478.53 3549.94   33.19 3611.98 3679.48   33.12
Permanent Ineff=
       F       F       F
#Block Obstruct= 2 ,-1
    2644 2683.47   35.17 7005.43 7041.97    34.5
Bank Sta=3522.08,3649.46
XS Rating Curve= 0
Skew Angle= 45
Exp/Cntr=.5,.3

Type RM Length L Ch R = 1 ,7216    ,953.23,949.58,663.49
BEGIN DESCRIPTION:
sv1d - structure valley 1 downstream from structure 1, overbank stations and elevations from DEM.    Blocked obstruction marks where x-section goes outside of drainage basin boundary.
END DESCRIPTION:
XS GIS Cut Line= 3
     3181058.767    13788161.452     3179771.771    13788117.714
     3177513.317    13785608.971
#Sta/Elev= 30
    3768   35.13 3791.61    34.4 3819.05   31.63 3943.34   32.38 4046.76   31.72
 4076.77   30.63 4106.79   31.98 4123.88   31.25 4152.91   32.04 4719.01   30.94
 4890.37   32.07 4903.14   33.36 4951.27    31.7 4980.43   21.97    5000   21.91
 5022.24   22.06 5055.78   30.81 5086.08   33.57 5088.71    31.6 5103.27   31.15
 5234.19   30.16 7256.24   28.63 7316.24   27.13 7364.95    28.7 7550.22   29.27
 8189.39   29.94    8240   29.25  8293.1    30.2 8324.96   29.22  8431.3    29.5
#Mann= 3 ,-1 , 0
    3768     .07       0 4951.27     .04       0 5055.78     .99       0
#XS Ineff= 2 , 0
       0 4903.14   33.36               0
Permanent Ineff=
       F       F
#Block Obstruct= 1 ,-1
 8362.62  8431.3      34
Bank Sta=4951.27,5055.78
XS Rating Curve= 0
Exp/Cntr=.3,.1

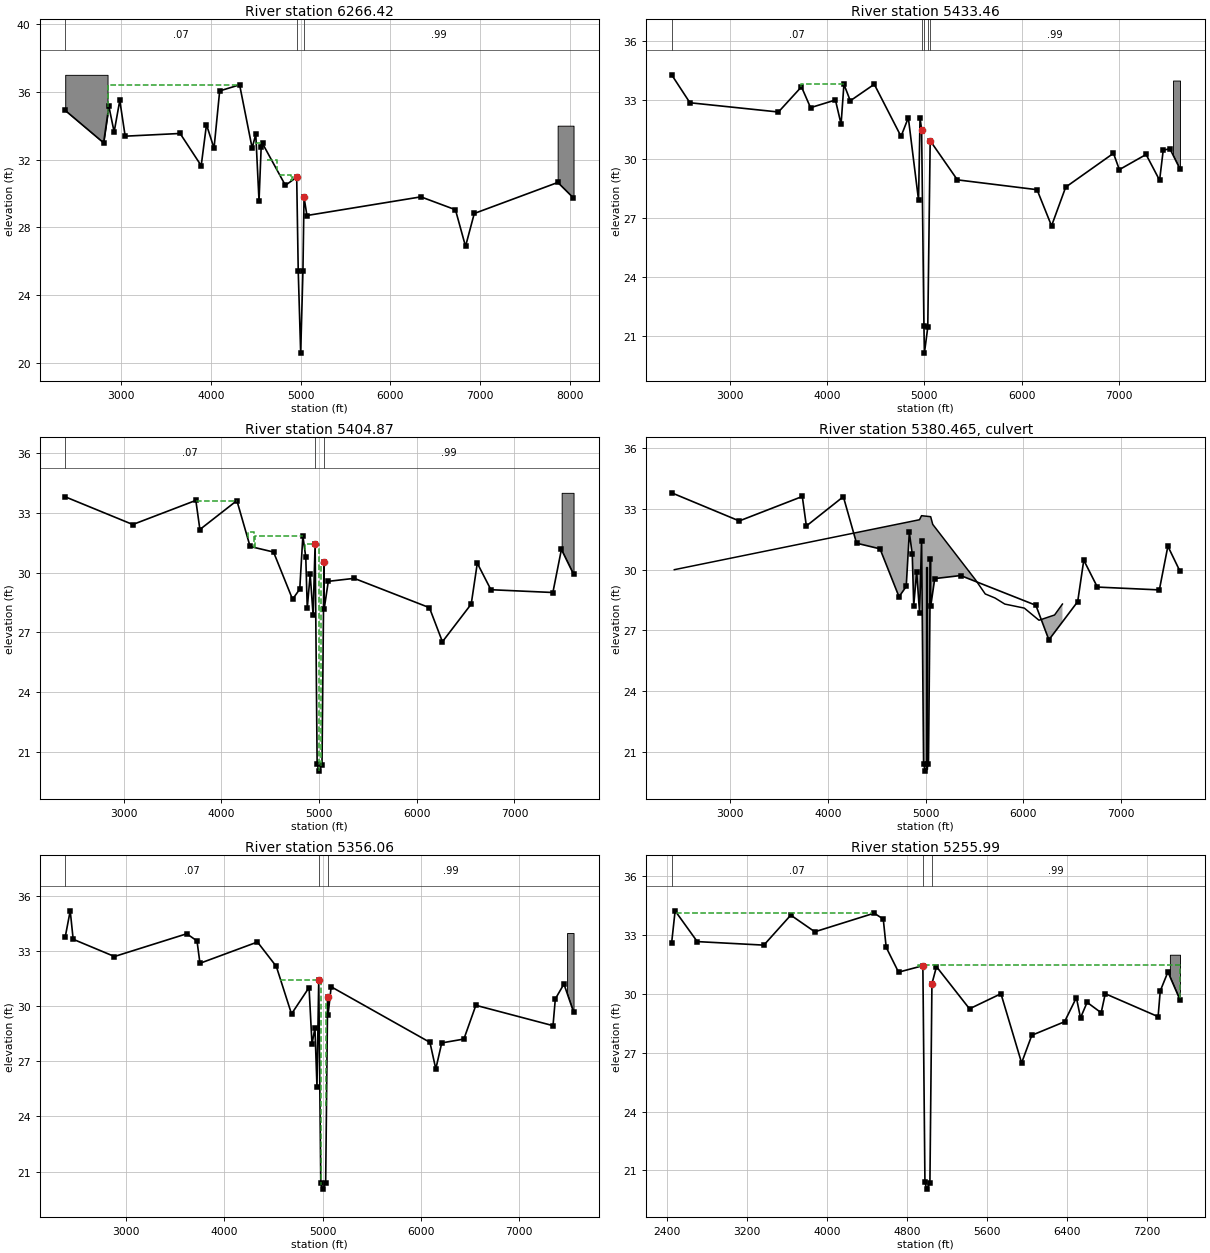
Type RM Length L Ch R = 1 ,6266.42 ,832.58,832.96,834.86
BEGIN DESCRIPTION:
v2 - x-section, left bank station to right bank station survey data, overbank station and elevations from DEM.  Blocked obstruction is end of drainage basin boundary.
END DESCRIPTION:
XS GIS Cut Line= 3
     3182513.299    13787225.515     3179078.441    13787154.798
     3177589.168    13785498.642
#Sta/Elev= 30
    2376    34.9 2803.64   32.99 2862.44   35.14 2921.25   33.63 2984.26   35.49
 3044.27   33.38 3656.38   33.54 3891.48   31.64 3950.28   34.06 4034.48   32.67
 4097.29   36.05 4319.54   36.41 4459.22   32.68 4499.58    33.5 4535.81   29.56
 4559.59   32.72 4574.59   32.95 4829.65   30.48 4955.62   30.96 4972.81   25.42
    5000   20.58 5025.12   25.42 5037.36   29.78  5069.7    28.7 6339.92    29.8
 6724.61   29.04 6837.05   26.88 6934.52   28.82 7865.63   30.65 8038.87   29.74
#Mann= 3 ,-1 , 0
    2376     .07       0 4955.62     .04       0 5037.36     .99       0
#XS Ineff= 5 ,-1
  2848.3 4319.54   36.41    4505 4574.59   32.95 4627.93 4739.63   31.96
    4775  4890.4   31.07    4900 4955.62   30.96
Permanent Ineff=
       F       F       F       F       F
#Block Obstruct= 2 ,-1
    2376 2847.74      37 7863.54 8040.59      34
Bank Sta=4955.62,5037.36
XS Rating Curve= 0
Exp/Cntr=.3,.1

Type RM Length L Ch R = 1 ,5433.46 ,28.54,28.59,29.05
BEGIN DESCRIPTION:
sv2 - 52ft upstream of s2u, overland stations and elev. from DEM. Composite manning's n value of 0.025 used for the channel area which consists of concrete side slopes with a highly vegetated channel bottom.  At structure, pictures indicate concrete lined side slopes and vegetation on channel bottom; therefore 0.015 for concrete sides and 0.04 for channel bottom.
END DESCRIPTION:
XS GIS Cut Line= 4
     3182492.466    13786406.872     3179906.279    13786339.012
     3178444.342    13786300.653     3177630.541    13785450.373
#Sta/Elev= 30
  2401.6   34.29  2589.3   32.87 3499.27    32.4 3736.16   33.68 3829.39   32.62
 4085.31   33.01 4143.39   31.78 4172.63   33.81 4238.11   32.97 4484.66   33.81
  4759.7   31.16 4834.73   32.11 4939.77   27.92  4955.3   32.09  4971.4   31.51
 4995.25   21.53    5000   20.14 5034.71   21.45 5059.54   30.94 5339.08   28.95
 6158.21   28.45 6307.37   26.61 6452.91   28.58 6944.08    30.3 7004.59   29.47
 7279.38   30.24 7418.34   28.93 7455.61   30.46 7524.43   30.53 7628.08    29.5
#Mann= 5 ,-1 , 0
  2401.6     .07       0  4971.4    .015       0 4995.25     .04       0
 5034.71    .015       0 5059.54     .99       0
#XS Ineff= 4 ,-1
    2400 3736.16   33.68 3736.16 4172.63   33.81    4638 4834.73   32.11
 4834.73  4955.3   32.09
Permanent Ineff=
       F       F       F       F
#Block Obstruct= 1 ,-1
 7556.26 7628.08      34
Bank Sta=4971.4,5059.54
XS Rating Curve= 0
Exp/Cntr=.5,.3

Type RM Length L Ch R = 1 ,5404.87 ,48.71,48.81,49.68
BEGIN DESCRIPTION:
s2-u upstream x-section of bridge structure 2, with 1-10x10 box culvert, with an additional 3-10x10 box culverts closed, overbank stations and elev. from DEM. Composite manning's n value of 0.025 used for the channel area which consists of concrete side slopes with a highly vegetated channel bottom.  At structure, pictures indicate concrete lined side slopes along the channel and vegetation within the channel; therefore 0.015 for sides and 0.04 for bottom
END DESCRIPTION:
XS GIS Cut Line= 4
     3182491.653    13786381.909     3179906.128    13786310.403
     3178485.586    13786271.115     3177665.019    13785402.104
#Sta/Elev= 30
  2401.6    33.8 3093.35   32.41 3738.59   33.62 3780.12   32.16 4158.75   33.61
  4293.8   31.31  4533.9   31.03 4728.68   28.66 4802.25   29.17 4834.01   31.84
 4864.02   30.76 4879.03   28.22 4909.04   29.91 4939.05   27.86 4959.45   31.44
 4980.11   20.39 4997.96   20.04 5029.86   20.37 5049.99   30.52 5052.77   28.19
 5094.29   29.56 5359.21   29.71 6129.21   28.24 6262.44   26.53 6557.21   28.42
 6619.45   30.47 6758.65   29.14 7392.98      29  7480.3   31.16  7604.4   29.92
#Mann= 3 ,-1 , 0
  2401.6     .07       0 4959.45    .015       0 5049.99     .99       0
#XS Ineff= 5 ,-1
  3739.7 4158.75   33.61    4270 4338.82   32.01  4348.8 4834.01   31.84
  4854.3 5000.77   31.44 5024.71 5049.97    30.5
Permanent Ineff=
       F       F       F       F       F
#Block Obstruct= 1 ,-1
 7482.89  7604.4      34
Bank Sta=4959.45,5049.99
XS Rating Curve= 0
Exp/Cntr=.5,.3

Type RM Length L Ch R = 2 ,5380.465,,,
BEGIN DESCRIPTION:
s2 - Dirt Road
Road profile based on survey data in the vicinity of the channel area, and from lidar in the overbank areas.
END DESCRIPTION:
Bridge Culvert--1,0,-1,-1, 0
Deck Dist Width WeirC Skew NumUp NumDn MinLoCord MaxHiCord MaxSubmerge Is_Ogee
10,17,2.6,0, 15, 15, 27.5, , .95, 0, 0,0,,
  2428.6 4937.99 4958.94 5052.63  5073.6    5511    5611    5711    5811    5911
    6011    6111    6161 6320.62    6401
      30   32.47   32.67   32.62   32.24    29.5    28.8    28.6    28.3    28.2
    28.1    27.7    27.5   27.76    28.3
      20      20      20      20      20
                                        
  2428.6 4937.99 4958.94 5052.63  5073.6    5511    5611    5711    5811    5911
    6011    6111    6161    6211    6401
      30   32.47   32.67   32.62   32.24    29.5    28.8    28.6    28.3    28.2
    28.1    27.7    27.5    27.7    28.3
      20      20      20      20      20
                                        
BR Coef=-1 , 1 , 1 ,, 0 ,,,.8,0,,0,
WSPro=,,,, 1 ,,,, 0 ,,,, 0 ,,,,-1 ,-1 ,-1 , 0 , 0 , 0 , 0 , 0
Culvert=2,10,10,17,.013,.7,.999,8,3,20.15,5011.31,20.14,5011.55,Culvert s2  , 0 ,10
Culvert Bottom n=.013
BC Design=,, 0 ,, 0 ,,,,,,
BC HTab HWMax=33.8

Type RM Length L Ch R = 1 ,5356.06 ,100.06,100.07,100.45
BEGIN DESCRIPTION:
s2-d - downstream x-section of bridge structure 2, with 1-10x10 box culvert, with an additional 3-10x10 box culverts closed, overbank stations and elev. from DEM. Composite manning's n value of 0.025 used for the channel area which consists of concrete side slopes with a highly vegetated channel bottom.  Manning's n value of 0.015 was used instead of the previous 0.025 because the picture shows on vegetation in the channel just d/s of the structure (assumed all concrete).
END DESCRIPTION:
XS GIS Cut Line= 4
     3182511.145    13786340.493      3179913.04    13786261.763
     3178526.843    13786219.757     3177713.288    13785353.835
#Sta/Elev= 30
  2378.7   33.78  2429.7   35.21 2459.71   33.66  2879.9   32.72 3615.97   33.96
 3720.29   33.57  3750.3   32.35 4335.57   33.51 4527.54   32.18  4682.3   29.59
 4860.81   31.03 4890.83   27.94 4920.84   28.83 4941.43   25.62 4959.45   31.44
 4980.11   20.39 4997.96   20.04 5029.86   20.37 5049.99   30.52 5053.72   29.51
 5085.92   31.07 6091.38   28.04 6150.88   26.59 6211.43   28.01 6436.82   28.22
 6558.77   30.06 7344.04   28.95 7367.67   30.41 7455.43   31.22 7552.98    29.7
#Mann= 3 ,-1 , 0
  2378.7     .07       0 4959.45    .015       0 5049.99     .99       0
#XS Ineff= 2 ,-1
  4562.8 4986.79   31.44 5038.16 5050.08   30.48
Permanent Ineff=
       F       F
#Block Obstruct= 1 ,-1
 7487.13 7552.98      34
Bank Sta=4959.45,5049.99
XS Rating Curve= 0
Exp/Cntr=.5,.3

Type RM Length L Ch R = 1 ,5255.99 ,354.82,354.2,351.81
BEGIN DESCRIPTION:
sv2-d - a copy of downstream x-section of bridge structure 2, with 1-10x10 box culvert, overbank stations and elev. from DEM not a copy.  Composite manning's n value of 0.025 used for the channel area which consists of concrete side slopes with a highly vegetated channel bottom.  Manning's n value of 0.04 was used instead of 0.025 because the concrete is only approx. 100' long.  Therefore, the section lies in manicured grass.
END DESCRIPTION:
XS GIS Cut Line= 4
     3182479.542    13786242.406     3179912.938    13786161.651
      3178533.89    13786118.261     3177761.557    13785291.775
#Sta/Elev= 30
  2449.7   32.62 2484.09   34.24 2705.24   32.67 3370.68   32.49 3639.66   34.02
 3879.78   33.17 4473.05   34.12 4563.75   33.82 4592.85   32.38 4716.35   31.11
 4959.45   31.44 4980.11   20.39 4997.96   20.04 5029.86   20.37 5049.99   30.52
 5095.38   31.39 5425.54   29.24 5739.59   30.01 5945.97   26.48 6047.81   27.89
  6374.9   28.58 6493.23   29.81 6534.57   28.78 6600.47   29.57  6740.8   29.04
 6781.86   30.01 7309.78   28.84    7331   30.15 7407.91   31.12 7528.49    29.7
#Mann= 3 ,-1 , 0
  2449.7     .07       0 4959.45     .04       0 5049.99     .99       0
#XS Ineff= 3 ,-1
    2490 4437.45   34.13 4912.94    4690    31.5    4917 4959.45   31.44
Permanent Ineff=
       F       F       F
#Block Obstruct= 2 ,-1
 3537.24  3614.7   30.72 7427.55 7528.49      32
Bank Sta=4959.45,5049.99
XS Rating Curve= 0
Exp/Cntr=.3,.1

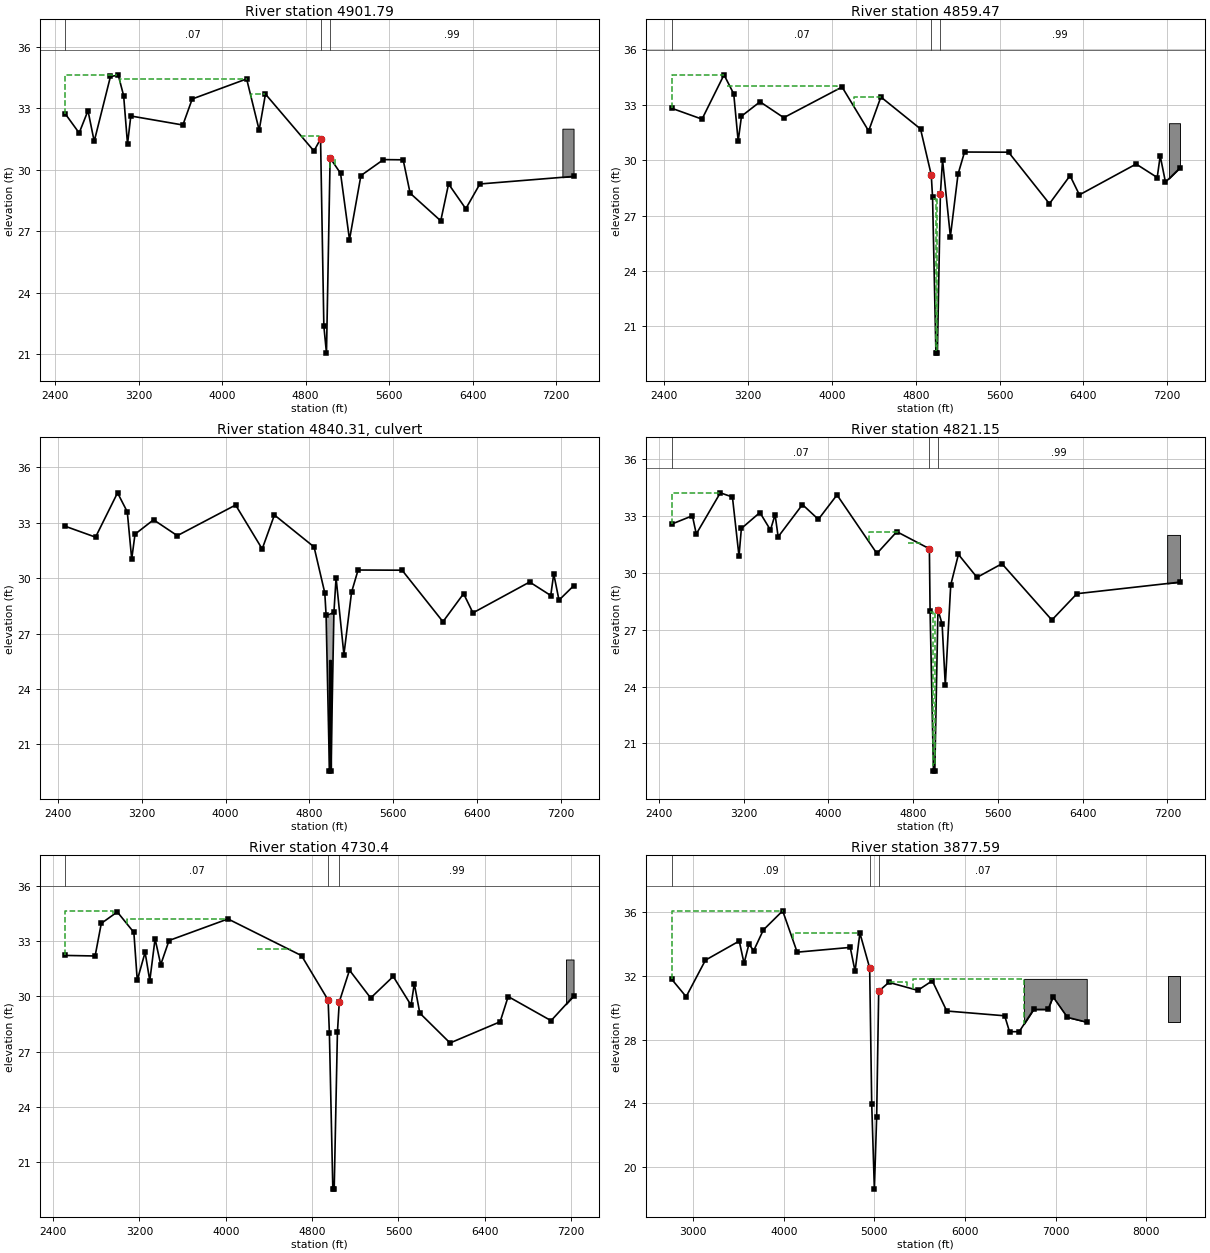
Type RM Length L Ch R = 1 ,4901.79 ,42.04,42.32,43.47
BEGIN DESCRIPTION:
sv3 -  upstream x-section of structure 3, 45 ft from s3u, overland station and elevation from DEM.  Blocked obstruction is the drainage basin boundary.
END DESCRIPTION:
XS GIS Cut Line= 4
     3182443.855     13785868.13     3179933.845    13785808.009
     3178285.596    13785768.528      3177802.93    13785243.506
#Sta/Elev= 30
  2495.6   32.73 2629.32   31.79 2714.04   32.88 2773.55   31.38 2929.41   34.55
 3004.43   34.61 3055.73   33.61 3092.91   31.25 3124.46   32.62 3623.44   32.18
 3713.01   33.45 4234.78   34.43 4354.82   31.93 4415.07   33.69 4879.97   30.91
 4943.27    31.5 4974.91   22.36    5000   21.04 5034.96   30.57 5135.04   29.82
 5220.65   26.58  5330.1   29.71 5546.26   30.49 5735.21   30.48 5801.89   28.85
 6095.31    27.5 6170.34    29.3 6335.38   28.09 6470.42    29.3 7368.22   29.67
#Mann= 3 , 0 , 0
  2495.6     .07       0 4943.27     .04       0 5034.96     .99       0
#XS Ineff= 5 ,-1
  2495.6 2991.41   34.63  3025.1 4234.78   34.43    4280 4414.61   33.69
    4770 4927.15   31.62 5033.25 5082.89   30.57
Permanent Ineff=
       F       F       F       F       F
#Block Obstruct= 1 ,-1
 7261.34 7368.22      32
Bank Sta=4943.27,5034.96
XS Rating Curve= 0
Exp/Cntr=.5,.3

Type RM Length L Ch R = 1 ,4859.47 ,38.01,38.32,39.77
BEGIN DESCRIPTION:
s3-u- upstream x-section of structure 3, bridge with 2- 6x6 .  Blocked obstruction is the drainage basin boundary.
END DESCRIPTION:
XS GIS Cut Line= 4
     3182464.688    13785835.976     3179933.708    13785765.742
     3178313.161    13785720.772     3177844.304    13785202.133
#Sta/Elev= 30
  2469.4   32.81 2759.03   32.22 2968.94   34.62 3061.89   33.59 3104.16   31.03
 3135.77   32.38 3312.77   33.16 3539.33    32.3 4095.97   33.96 4349.64   31.58
 4466.39   33.42 4844.83   31.69  4947.3    29.2 4959.66      28 4991.79   19.55
  5005.9   19.56 5034.35   28.14 5054.91   30.02 5129.83   25.86 5202.83   29.24
 5264.99   30.44 5685.15   30.43  6075.3   27.64 6272.17   29.16 6361.48   28.12
 6902.85   29.79 7104.16   29.06 7132.74   30.23 7182.89   28.81 7321.68   29.58
#Mann= 3 , 0 , 0
  2469.4     .07       0  4947.3     .04       0 5034.35     .99       0
#XS Ineff= 6 ,-1
  2469.4 2968.94   34.62    3000 4049.52   34.01  4209.2 4466.39   33.42
    4515 4552.67   32.69 4959.14 4991.29    27.9  5006.4 5034.37   28.07
Permanent Ineff=
       F       F       F       F       F       F
#Block Obstruct= 1 ,-1
    7216 7321.68      32
Bank Sta=4947.3,5034.35
XS Rating Curve= 0
Exp/Cntr=.5,.3

Type RM Length L Ch R = 2 ,4840.31 ,,,
BEGIN DESCRIPTION:
s3 - Dirt Road
END DESCRIPTION:
Bridge Culvert--1,0,-1,-1, 0
Deck Dist Width WeirC Skew NumUp NumDn MinLoCord MaxHiCord MaxSubmerge Is_Ogee
6,21,2.6,0, 4, 4, , , .95, 0, 0,0,,
 4959.66 4991.71  5005.9 5034.35
      28   28.04   28.08   28.14
      15      15      15      15
 4960.17 4992.01 5004.73 5034.58
      28   28.02   28.04   28.05
      15      15      15      15
BR Coef=-1 , 1 , 1 ,, 0 ,,,.8,0,,0,
WSPro=,,,, 1 ,,,, 0 ,,,, 0 ,,,,-1 ,-1 ,-1 , 0 , 0 , 0 , 0 , 0
Multiple Barrel Culv=2,6,6,21,.013,.5,1,10,1,19.55,19.54, 2,Culvert s3  , 0 ,6
 4994.79 4995.01  5002.9 5001.73
Culvert Bottom n=.013
BC Design=,, 0 ,, 0 ,,,,,,
BC HTab HWMax=34.4

Type RM Length L Ch R = 1 ,4821.15 ,90.43,90.75,91.54
BEGIN DESCRIPTION:
s3-d - downstream x-section of structure 3, bridge with 2- 6x6 box culverts, overland bank station and elevations from DEM
END DESCRIPTION:
XS GIS Cut Line= 4
 3182380.040641113785799.9694137     3179940.506    13785727.653
     3178333.741    13785675.565     3177885.677     13785160.76
#Sta/Elev= 30
  2521.8   32.57 2717.49   33.01 2753.92   32.05 2980.77   34.22 3095.08      34
 3157.11   30.88 3179.44   32.34  3354.3   33.18 3453.93   32.26 3497.55   33.07
 3526.63    31.9 3755.92    33.6  3906.1   32.82 4081.81   34.11  4458.4   31.02
 4646.16   32.17 4953.65   31.27 4960.17   28.01 4992.01   19.54 5004.73   19.55
 5034.58   28.05 5073.72    27.3 5103.73   24.07 5155.02   29.36  5227.7   30.97
    5403   29.76 5638.41   30.48 6109.26   27.51 6345.93    28.9 7318.45   29.51
#Mann= 3 , 0 , 0
  2521.8     .07       0 4953.65     .04       0 5034.58     .99       0
#XS Ineff= 7 ,-1
  2521.8 2980.77   34.22    2985 4081.81   34.11    4380 4661.32   32.17
    4750 4863.61   31.58 4960.14 4991.01   27.95 5006.08 5034.58   28.01
                   28.05
Permanent Ineff=
       F       F       F       F       F       F       F
#Block Obstruct= 1 ,-1
 7197.11 7318.45      32
Bank Sta=4953.65,5034.58
XS Rating Curve= 0
Exp/Cntr=.5,.3

Type RM Length L Ch R = 1 ,4730.4  ,853.25,852.81,844.67
BEGIN DESCRIPTION:
sv3-d - a copy of downstream x-section of structure 3, overland bank station and elevations from DEM not a copy
END DESCRIPTION:
XS GIS Cut Line= 4
      3182437.15    13785726.402     3179947.671    13785637.238
      3178354.83    13785581.056      3177927.05    13785126.282
#Sta/Elev= 30
  2512.7   32.22 2789.86   32.19 2847.04   33.96 2995.25   34.58 3148.74   33.47
 3180.11   30.87 3252.78   32.39 3296.25   30.85 3345.21   33.12 3397.68   31.72
 3474.66   33.03 4020.78    34.2 4701.84   32.21  4948.2    29.8 4960.17   28.01
 4992.01   19.54 5004.73   19.55 5034.58   28.05  5051.9    29.7 5146.36   31.42
 5342.48   29.91 5551.61   31.08 5716.66   29.52 5746.74   30.69 5797.75   29.09
 6077.98   27.47 6541.99   28.62 6616.51   29.99 7013.88   28.68 7221.96   30.01
#Mann= 3 , 0 , 0
  2512.7     .07       0  4948.2     .04       0  5051.9     .99       0
#XS Ineff= 4 ,-1
  2512.7 2954.96   34.64    3085 4005.63    34.2    4290 4591.01   32.59
Permanent Ineff=
       F       F       F       F
#Block Obstruct= 1 ,-1
 7151.83 7221.96      32
Bank Sta=4948.2,5051.9
XS Rating Curve= 0
Exp/Cntr=.3,.1

Type RM Length L Ch R = 1 ,3877.59 ,1035,1030,1019
BEGIN DESCRIPTION:
v3 - - x-section, left bank station to right bank station survey data, overbank station and elevations from DEM.  Blocked obstruction is the drainage basin boundary
END DESCRIPTION:
XS GIS Cut Line= 2
 3182233.9943189 13784825.512209      3177691.94      13784753.6
#Sta/Elev= 30
  2763.7    31.8  2923.4    30.7  3136.4      33  3509.1    34.2  3562.4    32.8
  3615.6      34  3668.9    33.6  3775.4    34.9  3988.4    36.1  4148.1    33.5
  4733.8    33.8    4787    32.3  4840.3    34.7  4948.1   32.51 4970.67   23.97
    5000    18.6 5025.23   23.15 5047.72   31.04  5159.8    31.6  5479.2    31.1
    5639    31.7  5798.7    29.8  6437.7    29.5  6490.9    28.5  6597.4    28.5
  6757.2    29.9  6916.9    29.9  6970.1    30.7  7129.9    29.4  7342.9    29.1
#Mann= 3 , 0 , 0
  2763.7     .09       0  4948.1     .04       0 5047.72     .07       0
#XS Ineff= 5 ,-1
  2763.7  3988.4    36.1 4098.15  4840.3    34.7 5047.72  5110.1   31.04
  5159.8  5355.1    31.6    5426  6650.7    31.8
Permanent Ineff=
       F       F       F       F       F
#Block Obstruct= 2 ,-1
  6650.7  7342.9   31.82 8239.67  8371.9   32.01
Bank Sta=4948.1,5047.72
XS Rating Curve= 0
Exp/Cntr=.3,.1

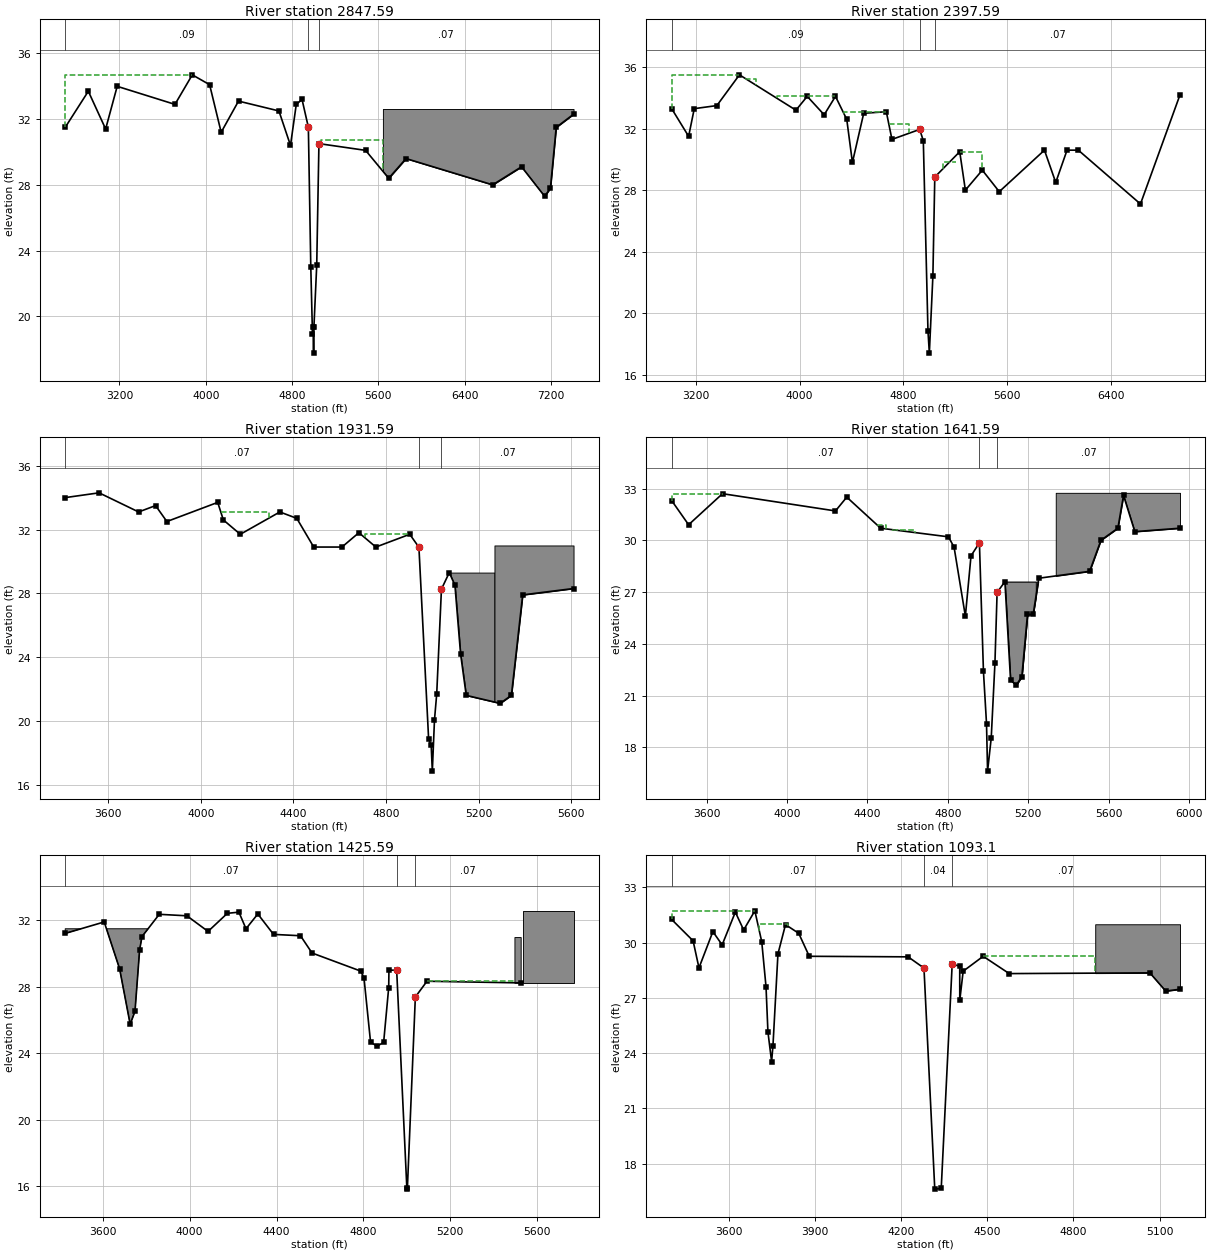
Type RM Length L Ch R = 1 ,2847.59 ,442,450,457
BEGIN DESCRIPTION:
v4 - - x-section, left bank station to right bank station survey data, overbank station and elevations from DEM.  Blocked obstruction marks where x-section goes outside of drainage basin boundary.
END DESCRIPTION:
XS GIS Cut Line= 2
      3182363.72      13783760.6 3177651.589606613783759.5244457
#Sta/Elev= 30
  2697.4    31.5  2911.6    33.7  3072.2    31.4  3179.3      34  3714.8    32.9
  3875.5    34.7  4036.1    34.1  4143.2    31.2  4303.9    33.1  4678.7    32.5
  4785.8    30.4  4839.4    32.9  4892.9    33.2 4951.44   31.51 4974.07   22.99
 4989.59    18.9 4995.64   19.37    5000   17.75 5003.26   19.37 5028.99    23.1
 5049.58   30.51    5482    30.1  5696.2    28.4  5856.8    29.6  6660.1      28
  6927.8    29.1    7142    27.3  7195.5    27.8  7249.1    31.5  7409.7    32.3
#Mann= 3 , 0 , 0
  2697.4     .09       0 4951.44     .04       0 5049.58     .07       0
#XS Ineff= 3 ,-1
  2697.4  3875.5    34.7 4067.66  4892.9    33.2 5068.59  5642.6   30.71
Permanent Ineff=
       F       F       F
#Block Obstruct= 1 ,-1
  5642.6  7409.7   32.62
Bank Sta=4951.44,5049.58
XS Rating Curve= 0
Exp/Cntr=.3,.1

Type RM Length L Ch R = 1 ,2397.59 ,579,466,290
BEGIN DESCRIPTION:
v5 - - x-section, left bank station to right bank station survey data, overbank station and elevations from DEM.  Blocked obstruction marks where x-section goes outside of drainage basin boundary.
END DESCRIPTION:
XS GIS Cut Line= 2
      3182048.03      13783370.5      3178132.15      13783254.4
#Sta/Elev= 30
  3014.3    33.3  3144.9    31.5  3188.4    33.3  3362.5    33.5  3536.6    35.5
  3971.9    33.2  4058.9    34.1  4189.5    32.9  4276.5    34.1  4363.6    32.6
  4407.1    29.8  4494.2      33  4668.3    33.1  4711.8    31.3 4925.89   31.95
 4953.52   31.21 4989.36   18.84    5000    17.4 5027.27   22.41 5041.95   28.85
  5234.1    30.5  5277.6      28  5408.2    29.3  5538.8    27.9    5887    30.6
    5974    28.5  6061.1    30.6  6148.1    30.6  6626.9    27.1  6931.6    34.2
#Mann= 3 , 0 , 0
  3014.3     .09       0 4925.89     .04       0 5041.95     .07       0
#XS Ineff= 7 ,-1
  3014.3  3536.6    35.5  3580.1  3667.2    35.2 3826.61  4276.5    34.1
  4341.5  4668.3    33.1 4687.34  4842.4    32.3  5103.5    5205    29.8
  5234.1  5408.2    30.5
Permanent Ineff=
       F       F       F       F       F       F       F
#Block Obstruct= 2 , 0
       0                  5408.2       0   34.24
Bank Sta=4925.89,5041.95
XS Rating Curve= 0
Exp/Cntr=.3,.1

Type RM Length L Ch R = 1 ,1931.59 ,290,290,290
BEGIN DESCRIPTION:
v6 - - x-section, left bank station to right bank station survey data, overbank station and elevations from DEM. Blocked obstruction used for detention pond area at and near the drainage area boundary.
END DESCRIPTION:
XS GIS Cut Line= 2
      3181331.88      13782024.2      3179478.52      13783203.5
#Sta/Elev= 30
  3413.6      34    3560    34.3  3730.9    33.1  3804.1    33.5  3852.9    32.5
  4072.6    33.7    4097    32.6  4170.2    31.7  4341.1    33.1  4414.3    32.7
  4487.5    30.9  4609.5    30.9  4682.7    31.8    4756    30.9  4902.4    31.7
 4942.05   30.89 4983.99   18.87 4995.09   18.47    5000   16.85 5009.32   20.06
 5018.98   21.69 5039.39   28.26  5073.3    29.3  5097.7    28.5  5122.1    24.2
  5146.5    21.6  5292.9    21.1  5341.7    21.6  5390.5    27.9  5610.2    28.3
#Mann= 3 , 0 , 0
  3413.6     .07       0 4942.05     .04       0 5039.39     .07       0
#XS Ineff= 4 ,-1
  3633.3  4072.6    33.7  4085.7  4292.2    33.1 4450.75  4682.7    31.8
  4707.2  4902.4    31.7
Permanent Ineff=
       F       F       F       F
#Block Obstruct= 2 ,-1
  5073.3  5268.5    29.3  5268.5  5610.2      31
Bank Sta=4942.05,5039.39
XS Rating Curve= 0
Exp/Cntr=.3,.1

Type RM Length L Ch R = 1 ,1641.59 ,133,216,321
BEGIN DESCRIPTION:
v7 -  x-section, left bank station to right bank station survey data, overbank station and elevations from DEM.  Blocked area near the main channel area represents a full detention pond area.   Blocked obstruction is the drainage basin boundary.
END DESCRIPTION:
XS GIS Cut Line= 2
      3181170.38       13781813.      3179016.53      13783139.8
#Sta/Elev= 30
  3425.8    32.3  3510.1    30.9  3678.8    32.7    4241    31.7  4297.2    32.5
  4465.9    30.7  4803.2    30.2  4831.3    29.6  4887.5    25.6  4915.6    29.1
 4957.42   29.85 4977.48    22.4 4992.75   19.37 4997.97   16.62 5016.13   18.53
 5034.62   22.87 5045.44   26.98  5084.3    27.6  5112.4    21.9  5140.5    21.6
  5168.6    22.1  5196.7    25.7  5224.8    25.7    5253    27.8  5505.9    28.2
  5562.2      30  5646.5    30.7  5674.6    32.6  5730.8    30.5  5955.7    30.7
#Mann= 3 , 0 , 0
  3425.8     .07       0 4957.42     .04       0 5045.44     .07       0
#XS Ineff= 6 ,-1
  3425.8  3678.8    32.7  3706.9  4297.2    32.5 4454.64    4494    30.9
  4522.1  4634.5    30.6 4652.88  4803.2    30.2  4803.2 4957.42   29.85
Permanent Ineff=
       F       F       F       F       F       F
#Block Obstruct= 3 ,-1
 5086.96 5251.72    27.6  5084.3 5237.99    27.6  5337.3  5955.7   32.75
Bank Sta=4957.42,5045.44
XS Rating Curve= 0
Exp/Cntr=.3,.1

Type RM Length L Ch R = 1 ,1425.59 ,567.18,332.49,143.93
BEGIN DESCRIPTION:
v8 - x-section, left bank station to right bank station survey data, overbank station and elevations from DEM.  Right overbank blocked obstruction is the drainage basin boundary;  left overbank blocked obstruction is a detention pond.
END DESCRIPTION:
XS GIS Cut Line= 4
     3181142.176    13781751.979     3180103.873    13782404.286
     3179420.211    13782459.759     3179283.009    13782582.925
#Sta/Elev= 30
  3427.3   31.22 3606.81   31.91 3677.67   29.09 3726.35   25.75 3748.53   26.53
 3769.87   30.23 3780.75   31.03 3860.23   32.37 3987.46   32.28 4084.78   31.34
 4173.68   32.43 4226.82    32.5 4259.45    31.5 4313.85   32.39 4386.25   31.16
 4510.25   31.08  4563.4   30.04 4787.65   28.95 4802.69   28.52 4832.79   24.67
 4862.89   24.43 4892.99   24.66 4916.32   27.96 4917.42   29.02 4953.04   28.99
    5000   15.82 5002.27   15.86 5038.93   27.39  5092.4   28.34 5523.79   28.24
#Mann= 3 , 0 , 0
  3427.3     .07       0 4953.04     .04       0 5038.93     .07       0
#XS Ineff= 2 ,-1
    4750 4917.42   29.02  5092.4    5495   28.34
Permanent Ineff=
       F       F
#Block Obstruct= 3 ,-1
  5532.3 5767.04   32.58  3427.3 3900.42    31.5    5495 5523.79      31
Bank Sta=4953.04,5038.93
XS Rating Curve= 0
Exp/Cntr=.3,.1

Type RM Length L Ch R = 1 ,1093.1  ,42.96,50.84,63.24
BEGIN DESCRIPTION:
sv4 - upstream section of IH-45, 50 ft from s4u, overbank stations and elevations from DEM.
END DESCRIPTION:
XS GIS Cut Line= 4
 3180532.441777613781392.6217126     3180261.184    13781635.508
     3179407.815    13782400.142     3179035.432    13782733.804
#Sta/Elev= 30
3399.964   31.263474.615    30.13495.062   28.633543.507    30.6 3575.81   29.88
3621.805   31.663650.799   30.693689.727   31.733713.803   30.053728.664   27.61
3735.367   25.153748.132   23.543752.809   24.38 3770.25   29.393796.595   30.98
3842.589   30.513879.386   29.264223.753   29.234279.056   28.624316.679   16.61
4339.193   16.654377.299   28.824403.661   28.734403.755   26.864415.611   28.45
4485.379   29.264576.086   28.32 5066.11   28.365121.312   27.375171.143   27.47
#Mann= 3 , 0 , 0
3399.964     .07       04279.056     .04       04377.299     .07       0
#XS Ineff= 7 ,-1
3399.9643689.727   31.733705.2033805.134   30.99
                                                4377.2994453.103   28.82
4485.3794875.723   29.26
Permanent Ineff=
       F       F       F       F       F       F       F
#Block Obstruct= 1 ,-1
4875.7235171.143      31
Bank Sta=4279.056,4377.299
XS Rating Curve= 0
Skew Angle= 30
Exp/Cntr=.5,.3