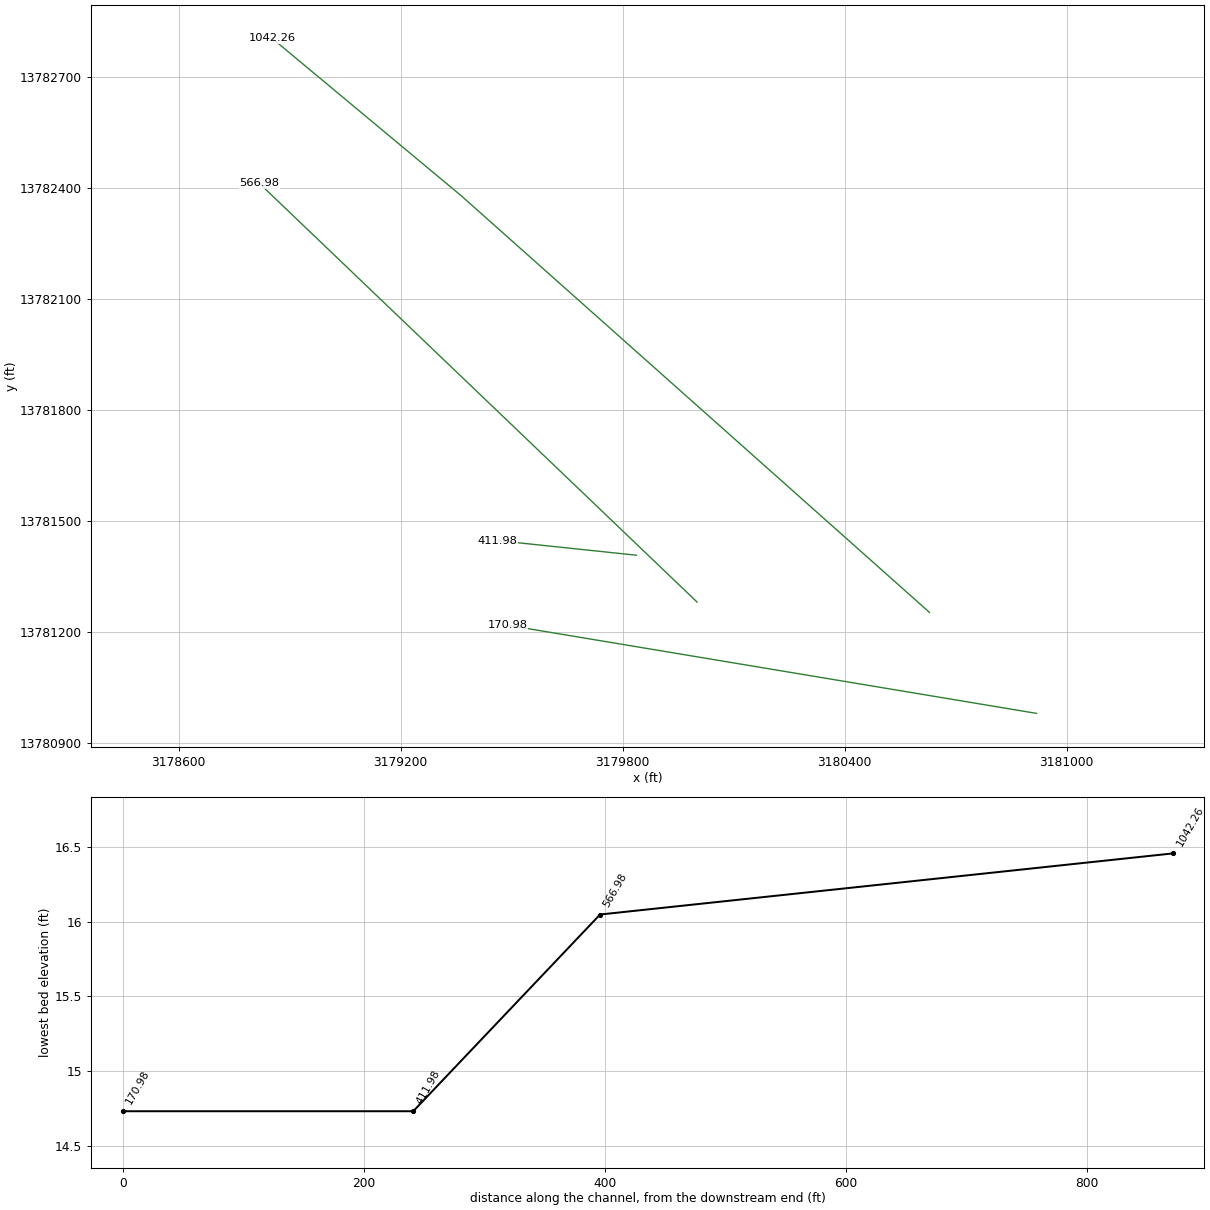
HEC-RAS study A119-05-00.prj: A119_05_00

--- A119-05-00.g06 (geometry) --- (continued)

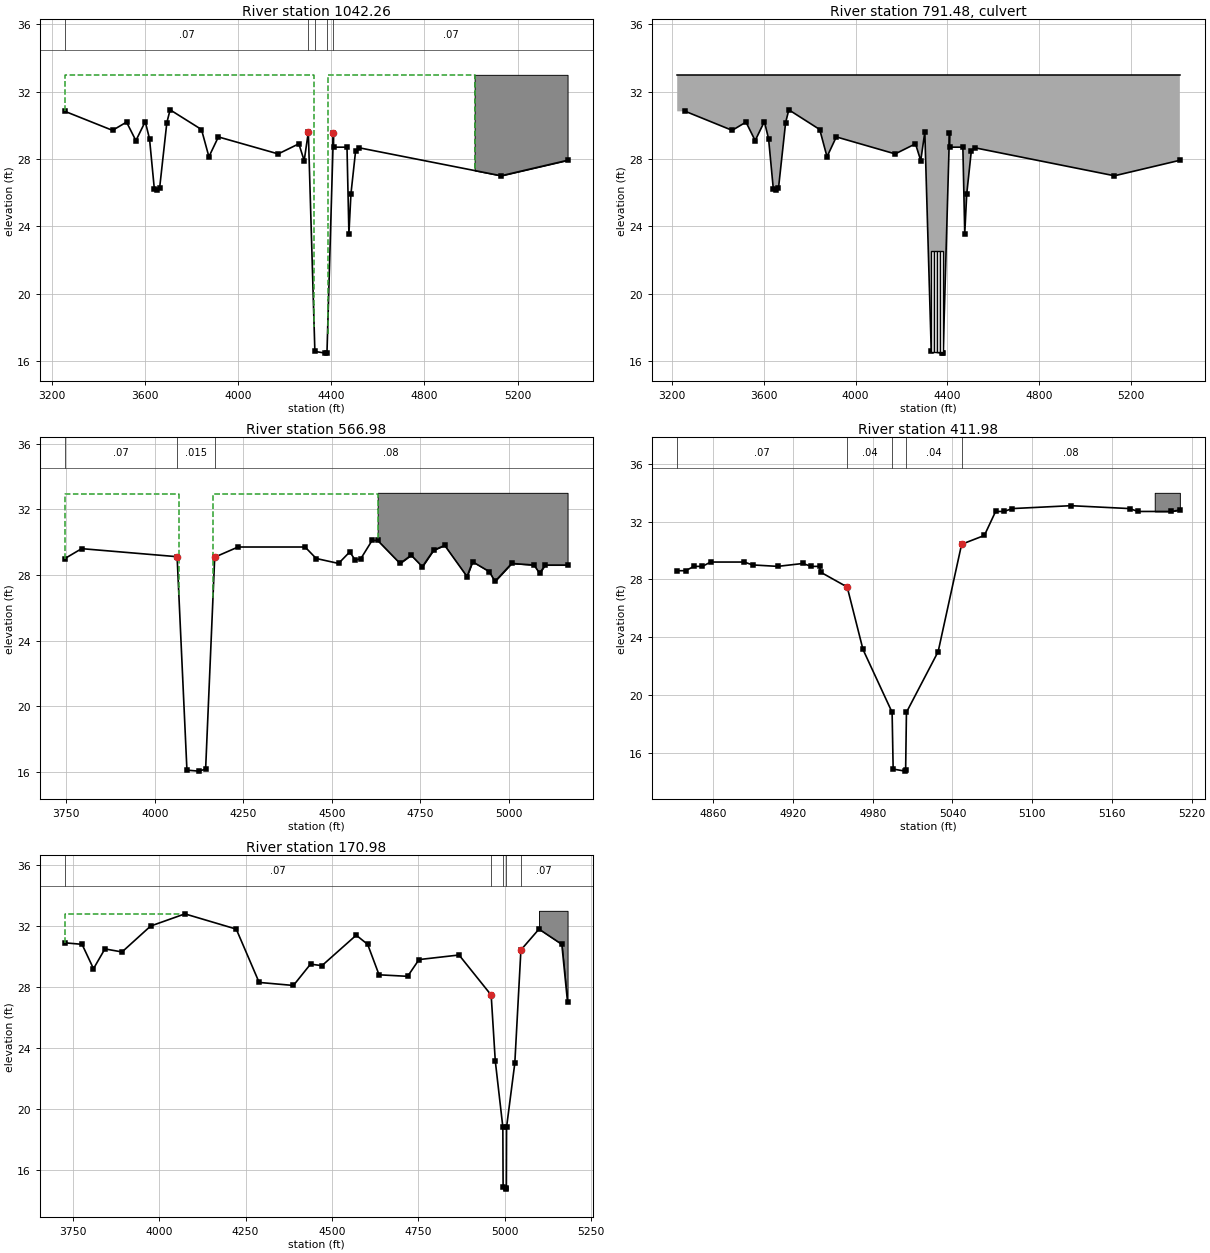
Type RM Length L Ch R = 1 ,1042.26 ,398.12,475.28,526.48
BEGIN DESCRIPTION:
s4-u - upstream section of IH-45, overbank stations and elevations from DEM, Box Culvert, 4 - 10 x 10. Composite manning's n value of 0.025 used for the channel area which consists of concrete side slopes with a highly vegetated channel bottom.  Did not assume composite n value as previously stated; entered actual n values for concrete side slopes and vegetated bottom.
END DESCRIPTION:
XS GIS Cut Line= 4
     3180629.407    13781253.717     3180255.703    13781585.899
     3179363.794    13782378.707 3178852.471079413782803.9312314
#Sta/Elev= 30
3257.051   30.833461.381    29.73521.591   30.193561.731   29.093601.861   30.22
3620.221    29.23640.871   26.223651.031   26.153663.451   26.253694.601   30.16
3708.611   30.923843.341   29.753875.221   28.133915.831   29.314172.721    28.3
4261.278    28.94284.228    27.94302.007   29.594330.127   16.564375.429   16.46
4382.045   16.484409.714   29.564410.581    28.74467.999    28.74476.261   23.56
4484.911   25.924504.981   28.484521.411   28.665129.621      27  5414.9   27.92
#Mann= 5 ,-1 , 0
3257.051     .07       04302.007    .015       04330.127     .04       0
4382.045    .015       04409.714     .07       0
#XS Ineff= 2 ,-1
3257.051 4326.93      33 4384.43    5016      33
Permanent Ineff=
       F       F
#Block Obstruct= 1 ,-1
    5016  5414.9      33
Bank Sta=4302.007,4409.714
XS Rating Curve= 0
Skew Angle= 30
Exp/Cntr=.5,.3

Type RM Length L Ch R = 2 ,791.48  ,,,
Node Photo=A119-05-S4p1.JPG
BEGIN DESCRIPTION:
s4 - IH 45
END DESCRIPTION:
Bridge Culvert--1,0,-1,-1, 0
Deck Dist Width WeirC Skew NumUp NumDn MinLoCord MaxHiCord MaxSubmerge Is_Ogee
6,443,2.6,30, 2, 2, 33, , .95, 0, 0,0,,
 3221.57  5414.9
      33      33
      15      15
 3746.37 5165.18
      33      33
      15      15
BR Coef=-1 , 1 , 1 ,, 0 ,,,.8,-1,,0,
WSPro=,,,, 1 ,,,, 0 ,,,, 0 ,,,,-1 ,-1 ,-1 , 0 , 0 , 0 , 0 , 0
Multiple Barrel Culv=2,6,12,443,.013,.7,1,8,3,16.52,16.12, 4,Culvert s4  , 0 ,6
 4335.93  4096.7 4348.83    4110    4362 4123.65 4375.43  4137.3
Culvert Bottom n=.013
BC Design=,, 0 ,, 0 ,,,,,,
BC HTab HWMax=31.1

Type RM Length L Ch R = 1 ,566.98  ,94,155,230
BEGIN DESCRIPTION:
s4-d- downstream section of IH-45, overbank stations and elevations from DEM, Box Culvert, 4 - 10 x 10.  Composite manning's n value of 0.025 used for the channel area which consists of concrete side slopes with a highly vegetated channel bottom.  Blocked obstruction marks where x-section goes outside of drainage basin boundary.  Manning's n value of 0.015 was used for the channel instead of the 0.025 because it looks like channel bottom is concrete (assumed all concrete).
END DESCRIPTION:
XS GIS Cut Line= 2
      3180001.22      13781281.6      3178817.59      13782412.7
#Sta/Elev= 30
3746.374      293793.659    29.64063.062   29.114090.775   16.114123.649   16.05
4143.524   16.174169.167   29.084235.072    29.74424.212    29.74455.735      29
4518.782    28.74550.306    29.44566.067    28.94581.916      294613.438    30.1
  4629.2    30.14692.247    28.7 4723.77    29.24755.293    28.54786.816    29.5
 4818.34    29.84881.387    27.94897.148    28.84944.433    28.24960.195    27.6
 5007.48    28.75070.527    28.65086.289    28.1 5102.05    28.6 5165.18    28.6
#Mann= 3 , 0 , 0
3746.374     .07       04063.062    .015       04169.167     .08       0
#XS Ineff= 2 ,-1
 3746.37 4068.06    32.9 4164.17  4629.2    32.9
Permanent Ineff=
       F       F
#Block Obstruct= 1 ,-1
 4629.22 5165.18      33
Bank Sta=4063.062,4169.167
XS Rating Curve= 0
Skew Angle= 30
Exp/Cntr=.5,.3

Type RM Length L Ch R = 1 ,411.98  ,241,241,241
Node Photo=A119-05-S4p6.JPG
BEGIN DESCRIPTION:
sv4d- channel data copied from  v9, overbank station and elevation from DEM;  blocked obstruction is the drainage basin boundary.
END DESCRIPTION:
XS GIS Cut Line= 2
       3179837.3      13781408.1      3179461.61      13781447.6
#Sta/Elev= 30
 4832.95    28.6 4839.25    28.6 4845.55    28.9 4851.85    28.9 4858.15    29.2
 4883.35    29.2 4889.65      29 4908.55    28.9 4927.45    29.1 4933.75    28.9
 4940.05    28.9 4940.81    28.5 4960.82   27.47 4972.69   23.15  4994.6    18.8
 4995.39   14.87 5004.49   14.73 5004.78   14.82 5005.38    18.8 5029.23      23
 5046.89   30.43    5064   31.04 5072.45    32.7 5078.75    32.7 5085.05    32.9
 5129.15    33.1 5173.25    32.9 5179.55    32.7 5204.75    32.7 5211.05    32.8
#Mann= 5 ,-1 , 0
 4832.95     .07       0 4960.82     .04       0  4994.6    .015       0
 5005.38     .04       0 5046.89     .08       0
#Block Obstruct= 2 ,-1
 5192.15 5211.05   33.99 5277.27 7066.12   27.67
Bank Sta=4960.82,5046.89
XS Rating Curve= 0
Exp/Cntr=.3,.1

Type RM Length L Ch R = 1 ,170.98  ,168.72,170.98,102.74
BEGIN DESCRIPTION:
v9- farthest downstream X-section, overbank stations and elevations from DEM;  blocked obstruction is the drainage basin boundary.
END DESCRIPTION:
XS GIS Cut Line= 2
      3180918.69       13780981.      3179488.38      13781219.1
#Sta/Elev= 30
  3727.1    30.9  3776.7    30.8  3809.8    29.2  3842.8    30.5  3892.4    30.3
  3975.1      32  4074.3    32.8    4223    31.8  4289.2    28.3  4388.4    28.1
  4437.9    29.5    4471    29.4  4570.2    31.4  4603.3    30.8  4636.3    28.8
    4719    28.7    4752    29.8  4867.8    30.1 4960.82   27.47 4972.69   23.15
  4994.6    18.8 4995.39   14.87 5004.49   14.73 5004.78   14.82 5005.38    18.8
 5029.23      23 5046.89   30.43  5099.2    31.8  5165.3    30.8  5181.9      27
#Mann= 5 ,-1 , 0
  3727.1     .07       0 4960.82     .04       0  4994.6    .015       0
 5004.78     .04       0 5046.89     .07       0
#XS Ineff= 1 ,-1
  3727.1  4057.7    32.8
Permanent Ineff=
       F
#Block Obstruct= 1 ,-1
  5099.2  5181.9      33
Bank Sta=4960.82,5046.89
XS Rating Curve= 0
Exp/Cntr=.3,.1

Chan Stop Cuts=-1